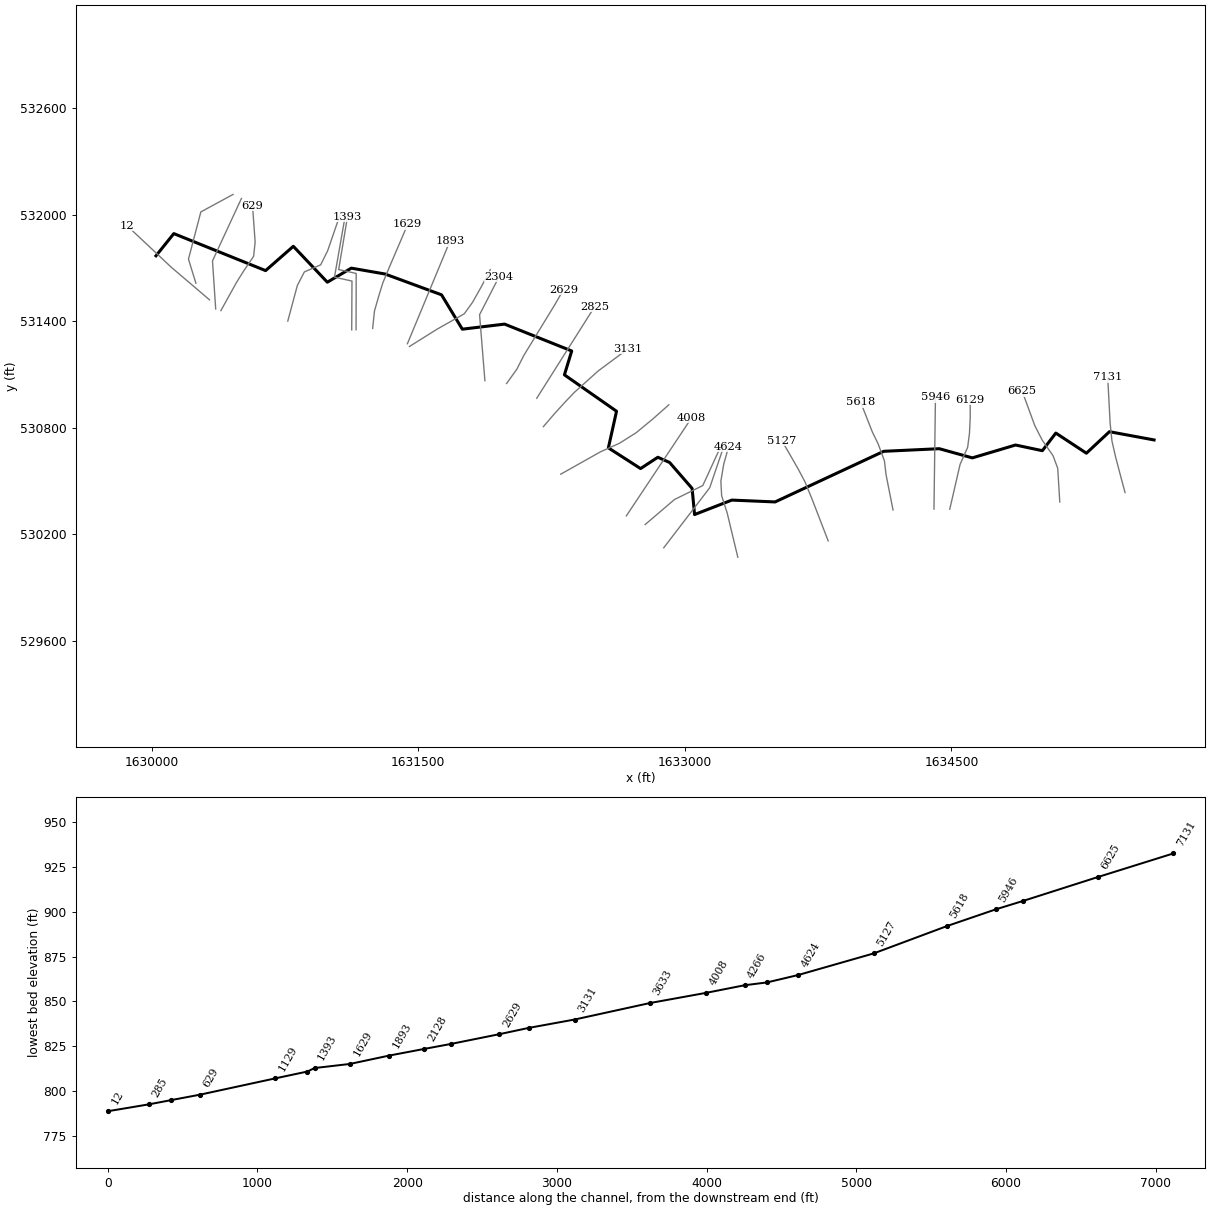
--- WilsonRn.prj (project) ---

Proj Title=WilsonRn
Current Plan=p01
Default Exp/Contr=0,0
English Units
Geom File=g01
Flow File=f01
Plan File=p01
Background Map Layer=Inundation Boundary (P100yr Value_0)
BEGIN DESCRIPTION:
---------- MODELED AS PART OF WVEM CTP PROGRAM, 2025----------
Stream Name: Wilson Run
Flood Zone: AFH
Marshall County, WV
HEC-RAS Version: RAS 6.6
Vertical Datum: NAVD88
Projection: NAD 1983 StatePlane West Virginia N FIPS 4701 (US Feet)
Terrain: 1-meter West Virginia FEMA R3 South Central (collected 2018-2019)
Land Use: 2024 NLCD
Hydrologic Method:
Duda et al., "Estimation of magnitude and frequency of floods for rural, unregulated streams in and near Virginia and West Virginia." September 8, 2025.
Additional Model Notes:
None
END DESCRIPTION:
DSS Export Rating Curves= 0
DSS Export Rating Curve Sorted= 0
DSS Export Volume Flow Curves= 0
DXF OffsetX= 0
DXF OffsetY= 0
DXF ScaleX= 0
DXF ScaleY= 0

--- WilsonRn.p01 (plan) ---

Plan Title=Floodplain
Program Version=6.60
Short Identifier=Floodplain
Geom File=g01
Flow File=f01
Subcritical Flow
K Sum by GR= 0
Std Step Tol= 0.01
Critical Tol= 0.01
Num of Std Step Trials= 20
Max Error Tol= 0.3
Flow Tol Ratio= 0.001
Split Flow NTrial= 30
Split Flow Tol= 0.02
Split Flow Ratio= 0.02
Log Output Level= 0
Friction Slope Method= 1
Unsteady Friction Slope Method= 2
Unsteady Bridges Friction Slope Method= 1
Parabolic Critical Depth
Global Vel Dist= 0 , 0 , 0
Global Log Level= 0
CheckData=False
Encroach Param=-1 ,0,0, 0
Flow Ratio Tolerance=0.1
Flow Ratio Min Ratio=0.5
Flow Ratio Max Ratio=4
Flow Ratio Max Iterations= 10
Mapping Interval=1HOUR
Computation Time Step Use Courant=        0
Computation Time Step Use Time Series=    0
Computation Time Step Count To Double=0
Computation Time Step Max Doubling=0
Computation Time Step Max Halving=0
Computation Time Step Residence Courant=0
Run HTab= 0
Run UNet= 0
Run Sediment= 0
Run PostProcess= 0
Run WQNet= 0
Run RASMapper= 0
UNET Theta= 0
UNET Theta Warmup= 0
UNET ZTol= 0
UNET ZSATol= 0
UNET MxIter= 0
UNET Max Iter WO Improvement= 0
UNET MaxInSteps= 0
UNET DtIC= 0
UNET DtMin= 0
UNET MaxCRTS= 0
UNET WFStab= 0
UNET SFStab= 0
UNET WFX= 1
UNET SFX= 1
UNET Gravity=32.17405
UNET 1D Methodology=Finite Difference
UNET DSS MLevel= 1
UNET Pardiso=0
UNET DZMax Abort= 0
UNET Use Existing IB Tables= 0
UNET Froude Reduction=False
UNET Froude Limit= 0
UNET Froude Power= 0
UNET D1 Cores= 0
UNET WindReference=Eulerian
UNET WindDragFormulation=Hsu (1988)
UNET D2 Coriolis=0
UNET D2 Cores= 0
UNET D2 Theta= 1
UNET D2 Theta Warmup= 1
UNET D2 Z Tol= 0.01
UNET D2 Volume Tol= 0.01
UNET D2 Max Iterations= 20
UNET D2 Advanced Convergence=0
UNET D2 WS Max Tol=0.15
UNET D2 WS RMS Tol=0.002
UNET D2 WS Stall Tol=1
UNET D2 Equation= 0
UNET D2 RampUpFraction=0.1
UNET D2 TimeSlices= 1
UNET D2 Turbulence Formulation=Non-Conservative (original)
UNET D2 Eddy Viscosity=0.3
UNET D2 Transverse Eddy Viscosity=0.1
UNET D2 Smagorinsky Mixing=0
UNET D2 BCVolumeCheck=0
UNET D2 Cores=0
UNET D2 SolverType=PARDISO (Direct)
UNET D2 Minimum Iterations= 3
UNET D2 Maximum Iterations= 30
UNET D2 Restart Number= 10
UNET D2 Relaxation Coeff=1.3
UNET D2 SOR Precondition Iterations= 10
UNET D2 ILUT Maximum Fill= 8
UNET D2 ILUT Tolerance=1E-08
UNET D2 Convergence Tolerance=0.00001
PS Theta= 1
PS WS Tol= 0.01
PS Volume Tol= 0.01
PS Max Iterations= 20
PS Equation= 0
PS Advance Time Step=-1
PS Target Courant=0.9
PS Time Slices= 1
PS Iterate With 2D=0
PS Project Initial WSE from DS=-1
PS Ramp Up Initial WSE from US=-1
PS Cores=0
UNET D1D2 MaxIter= 0
UNET D1D2 ZTol=0.01
UNET D1D2 QTol=0.1
UNET D1D2 MinQTol=1
Write IC File= 0
Write IC File at Fixed DateTime=0
Write IC File at Sim End=0
Echo Input=False
Echo Parameters=False
Echo Output=False
Write Detailed= 0
HDF Write Warmup=0
HDF Write Time Slices=0
HDF Flush=0
HDF Compression= 1
HDF Chunk Size= 1
HDF Spatial Parts= 1
HDF Use Max Rows=0
HDF Fixed Rows= 1
Calibration Method= 0
Calibration Iterations= 20
Calibration Max Change=0.05
Calibration Tolerance=0.2
Calibration Maximum=1.5
Calibration Minimum=0.5
Calibration Optimization Method= 1
WQ AD Non Conservative
WQ ULTIMATE=-1
WQ Max Comp Step=1HOUR
WQ Output Interval=15MIN
WQ Output Selected Increments= 0
WQ Create Restart=0
WQ Fixed Restart=0
WQ System Summary=0
WQ Write To DSS=0
Sorting and Armoring Iterations= 10
XS Update Threshold= 0.02
Bed Roughness Predictor= 0
Processes Affected by Predictor=Sediment Only
Hydraulics Update Threshold= 0.02
Energy Slope Method= 1
Volume Change Method= 1
Sediment Retention Method= 0
Sediment TS Multiplier= 1
Warm Up Method= 0
XS Weighting Method= 0
Number of US Weighted Cross Sections= 1
Number of DS Weighted Cross Sections= 1
Upstream XS Weight=0
Main XS Weight=1
Downstream XS Weight=0
Number of DS XS's Weighted with US Boundary= 1
Upstream Boundary Weight= 1
Weight of XSs Associated with US Boundary= 0
Number of US XS's Weighted with DS Boundary= 1
Downstream Boundary Weight= 0.5
Weight of XSs Associated with DS Boundary= 0.5
Percentile Method= 0
Sediment Output Level= 3
Mass or Volume Output= 0
Output Increment Type= 1
Profile and TS Output Increment= 1
Transport Output Increment 1
XS Output Flag= 0
XS Output Increment= 10
Read HDF5 Sediment Hotstart= 0
Sediment Hotstart Type= 0
Write Gradation File= 0
Read Gradation Hotstart= 0
Write HDF5 File= 1
Write Binary Output= 1
Write DSS Sediment File= 0
DSS Sediment Output Type= 1
SV Curve= 0
Specific Gage Flag= 0
Subcell Erosion Methods= 0
Subcell Deposition Methods= 0
Advection Scheme= 1
Matrix Solver= 0
Implicit Weighting Factor= 1
Maximum Outer Loop Convergence Iterations= 5
Convergence Maximum Absolute= 0.001
Convergence RMSE= 0.0001
Grain Fractions Max Abs Error= 0.001
Max Subgrid Regions= 1
Max Subgrid Length Scale= 3.402823E+38
Initial Layer Thickness= 3
Min Layer Thickness= 0.1
Max Layer Thickness= 6
Number of Layers= 5

--- WilsonRn.f01 (steady flow) ---

Flow Title=Flow
Program Version=6.60
Number of Profiles= 1
Profile Names=P100yr
River Rch & RM=WilsonRun,Main            ,7131
     729
River Rch & RM=WilsonRun,Main            ,5127
     846
River Rch & RM=WilsonRun,Main            ,4266
     953
River Rch & RM=WilsonRun,Main            ,12
    2470
Boundary for River Rch & Prof#=WilsonRun,Main            , 1
Up Type= 0
Dn Type= 1
Dn Known WS=794.6
DSS Import GetInterval= 0
DSS Import GetPeak= 0
DSS Import FillOption= 0

--- WilsonRn.g01 (geometry) ---

Geom Title=Geometry
Program Version=6.60

River Reach=WilsonRun       ,Main
Reach XY= 30
     1635640.448      530731.582     1635389.269      530778.007
     1635259.735      530656.944     1635087.661      530770.264
     1635011.831      530671.168     1634861.032      530703.051
      1634618.03      530630.668     1634431.702      530682.356
     1634119.266      530667.617     1633508.131      530382.768
      1633264.62      530393.159     1633054.987      530311.749
     1633041.188      530458.793     1632914.571      530604.745
     1632848.357      530634.163      1632751.19      530570.485
     1632570.058      530686.989     1632615.914      530893.078
     1632322.709      531097.905      1632363.82      531232.239
     1631986.189      531383.292     1631748.258      531354.838
     1631631.237      531548.161     1631313.401      531665.258
      1631123.51      531698.236     1630988.647        531619.2
     1630797.368      531821.106     1630641.314      531684.366
     1630124.894      531892.564     1630024.582      531767.672

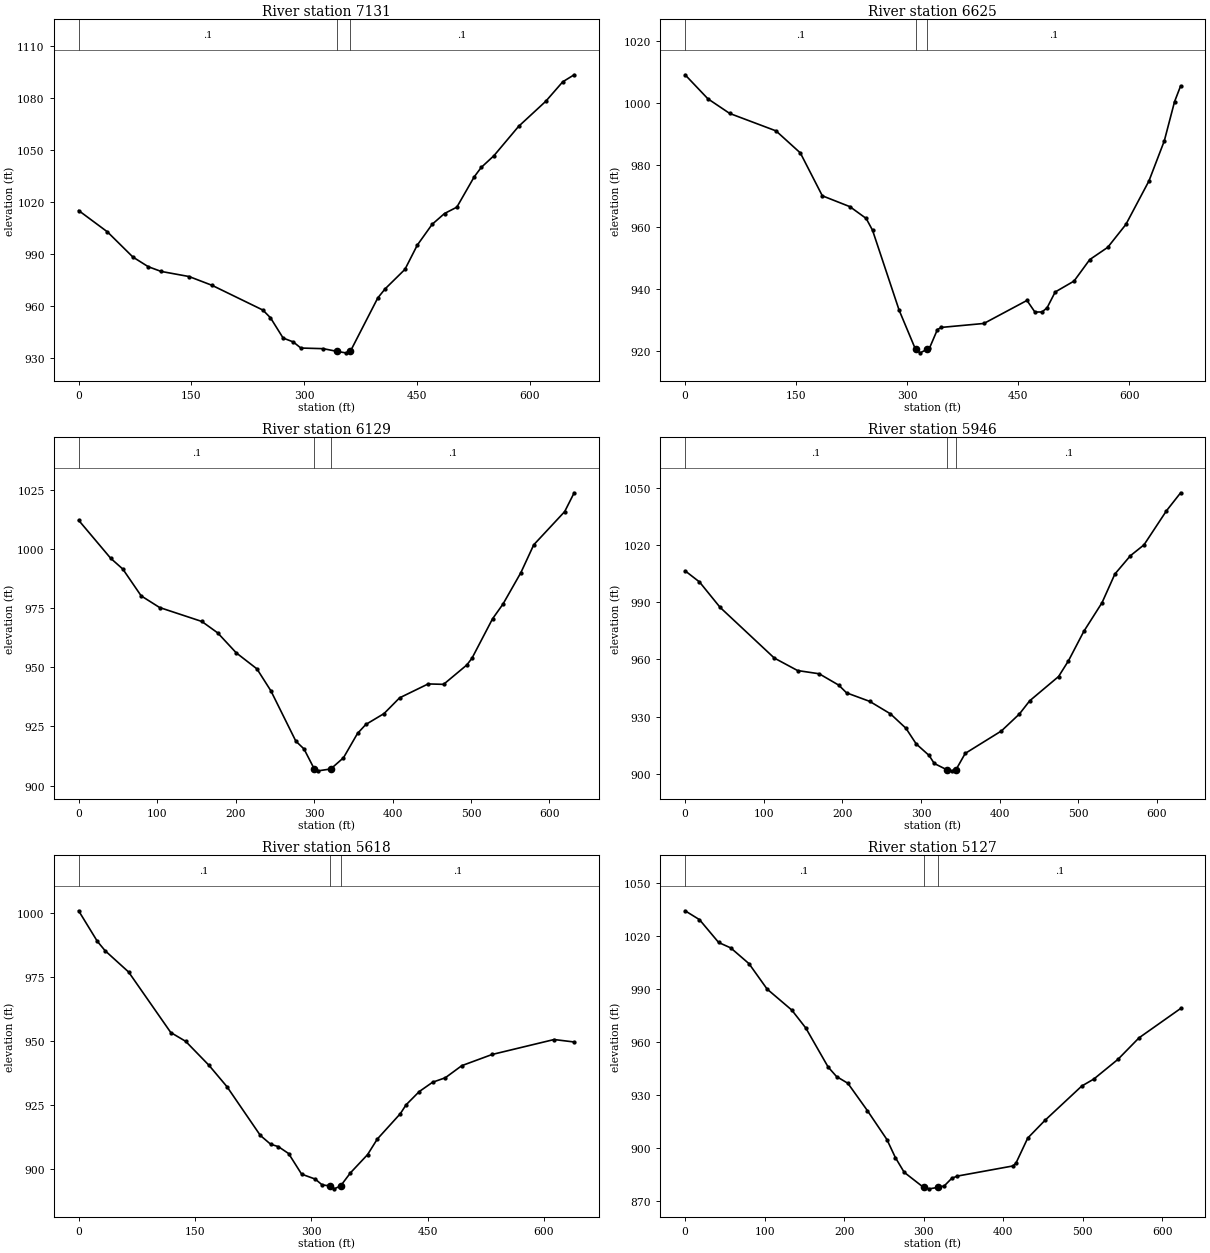
Type RM Length L Ch R = 1 ,7131    ,501.3,505.8,507.5
XS GIS Cut Line= 6
1635477.09407122530435.4181012211635449.95009664530537.022556812
1635423.91898072530636.3002453891635403.46495339530725.604200646
1635393.08931798530828.2775517261635379.62280947531084.173365399
#Sta/Elev= 30
       0 1014.91    38.3 1002.58    72.2  988.03    92.6  982.46   109.6  979.75
   146.9  976.78   177.4  971.71     245  957.42   255.1  952.96   271.9  941.27
   285.4  939.01   295.5  935.49   325.2  935.13  343.62933.5632   354.9  932.72
  361.28 933.564   397.8  964.45   407.6   969.7   433.9  980.94   450.3  994.93
   470.1 1006.97   486.5 1013.19   502.9 1016.86   525.9  1034.3   535.3 1039.79
   552.2 1046.57     585 1063.51   621.2 1078.03   643.7 1089.25   658.9 1093.31
#Mann= 3 ,-1,0
       0      .1       0  343.62    .045       0  361.28      .1       0
Bank Sta=343.62,361.28
XS Rating Curve= 0 ,0
Exp/Cntr(USF)=0,0
Exp/Cntr=0.3,0.1

Type RM Length L Ch R = 1 ,6625    ,501.9,496.1,482.4
XS GIS Cut Line= 6
1635109.92551422530382.5993092211635098.37829322530572.048733473
1635072.06043246530642.7920303051635010.76232672 530730.94900623
1634968.89036322530813.1588155631634898.74220955 531005.08920598
#Sta/Elev= 30
       0  1009.2    30.8 1001.45    60.3  996.72   122.8   991.1   155.7  983.98
   185.4  970.15   222.6  966.65   244.6  962.85   253.2  959.06   289.2  933.22
  311.34920.5867   317.6  919.48  326.73920.5877     330  920.91   340.9  926.99
     346  927.68   403.7  928.96   461.9  936.39   472.6  932.64   482.3  932.67
   489.1  934.03     500  939.11   525.5  942.64   546.7  949.57     571  953.52
   595.5   960.9   626.7  974.95   647.4  987.85   661.3 1000.54   669.5 1005.61
#Mann= 3 ,-1,0
       0      .1       0  311.34    .045       0  326.73      .1       0
Bank Sta=311.34,326.73
XS Rating Curve= 0 ,0
Exp/Cntr(USF)=0,0
Exp/Cntr=0.3,0.1

Type RM Length L Ch R = 1 ,6129    ,175.5,182.6,182.7
XS GIS Cut Line= 6
1634490.86343214530341.8867922281634549.09297447 530594.58576189
1634591.53088172530690.0301248131634601.82712097 530769.31933631
1634606.11746672530860.4605582211634605.41077521530956.938383639
#Sta/Elev= 30
       0 1012.08    40.9  995.99    56.3  991.46    79.7  980.13   103.2  975.21
     157  969.32   177.2   964.5   200.9  956.05   227.2   949.3     245  940.02
   276.8  918.76   287.2  915.47  300.31907.0063   305.2  906.22  321.27 907.007
   337.5  911.74   355.4  922.02     366  925.81   389.2  930.41     409  937.05
   445.4  942.93   465.1  942.76   494.7  950.94   501.3  953.82   527.5  970.46
   540.7  976.62   563.6  989.96     580 1001.71   619.4 1015.73   631.5 1023.68
#Mann= 3 ,-1,0
       0      .1       0  300.31    .045       0  321.27      .1       0
Bank Sta=300.31,321.27
XS Rating Curve= 0 ,0
Exp/Cntr(USF)=0,0
Exp/Cntr=0.3,0.1

Type RM Length L Ch R = 1 ,5946    ,323.9,328.3,329.1
XS GIS Cut Line= 2
1634402.07050001530342.5818941041634410.37444899530972.644023516
#Sta/Elev= 30
       0  1006.5    18.3 1000.66    44.5  987.32   113.4  960.72     143  954.16
   170.5  952.46   195.4  946.49   205.3  942.45   234.8  937.96   261.1  931.43
   280.8  923.86   293.9  915.62   310.3  909.57   316.8  905.38   332.7902.1033
   339.8  901.51  344.45902.1118   356.2  910.67   402.2  922.45   425.1  931.36
   438.2  938.29   474.9  951.02   487.5   959.3     507  974.73   530.1  989.74
   546.5 1004.82   566.2 1014.42   583.5 1020.13   612.1 1038.03   630.1 1047.47
#Mann= 3 ,-1,0
       0      .1       0   332.7    .045       0  344.45      .1       0
Bank Sta=332.7,344.45
XS Rating Curve= 0 ,0
Exp/Cntr(USF)=0,0
Exp/Cntr=0.3,0.1

Type RM Length L Ch R = 1 ,5618    ,489.1,490.7,488.7
XS GIS Cut Line= 6
1634171.70462164530337.3054365661634132.33757439530536.319802314
1634123.27427231530613.9180723131634088.30813488530708.609812066
 1634055.4338568530776.1342833041633988.84868814530945.283879399
#Sta/Elev= 30
       0 1000.75    24.1  988.82    34.2  985.13    64.4  976.84   118.8  953.18
     138  949.74     168  940.39   191.3     932   234.3  912.96   247.5  909.54
   257.5  908.59   270.7   905.9   287.5  897.84     305  895.92   313.8  893.68
  324.08893.2078   329.5   892.1  337.68893.2064   350.5  898.37   372.5  905.46
   385.1  911.56   414.8  921.48   422.1   924.9   439.1  930.09   456.3  933.74
   472.8  935.51     494  940.23   533.1   944.6     613  950.44   638.9  949.48
#Mann= 3 ,-1,0
       0      .1       0  324.08    .045       0  337.68      .1       0
Bank Sta=324.08,337.68
XS Rating Curve= 0 ,0
Exp/Cntr(USF)=0,0
Exp/Cntr=0.3,0.1

Type RM Length L Ch R = 1 ,5127    ,502.4,503.6,499.3
XS GIS Cut Line= 6
1633806.87168989530163.5610333981633714.51885623530402.590739056
1633675.89491773530496.3999346491633639.33298297530565.689822316
1633594.36588131530644.3389432281633546.03920631530727.558921143
#Sta/Elev= 30
       0 1034.51    18.1 1029.47    42.2 1016.52    57.4 1013.44    80.3 1004.52
   103.1  990.09   134.1  978.19   151.7  968.02   179.8  945.88   190.4  940.47
   204.6  936.66   229.1  921.18   253.7  904.74   264.3  894.53   275.4  886.16
  299.69877.6237   306.9  876.78  317.96877.6237   325.7  878.41   335.3  882.81
   342.4  884.03   412.2  889.77   415.9  891.36   430.7  905.58   452.2  915.56
   498.6  935.09   513.8  939.07   544.1  950.23   570.6  962.44   622.9  979.09
#Mann= 3 ,-1,0
       0      .1       0  299.69    .045       0  317.96      .1       0
Bank Sta=299.69,317.96
XS Rating Curve= 0 ,0
Exp/Cntr(USF)=0,0
Exp/Cntr=0.3,0.1

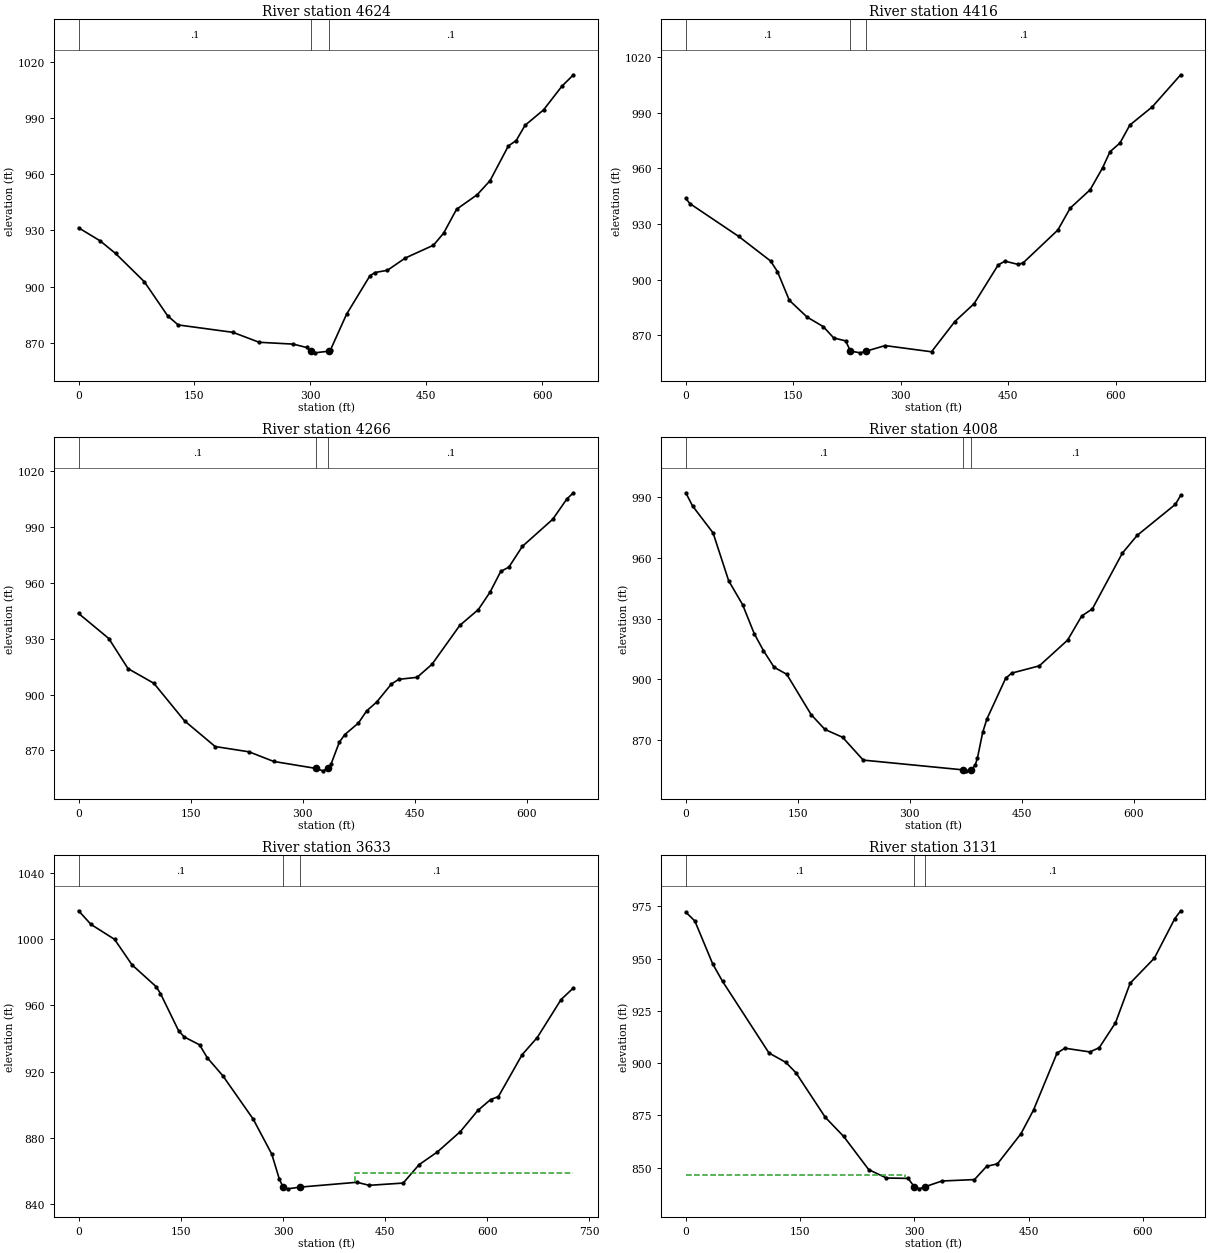
Type RM Length L Ch R = 1 ,4624    ,221.7,208.1,201.4
XS GIS Cut Line= 6
1633298.34383555530071.3663358991633238.56639606530320.538737804
1633207.32466064 530417.734737651633203.03923614530499.865806982
1633219.14255039530595.7110877341633246.89544764530694.656755984
#Sta/Elev= 30
       0  931.42    27.7  924.51    47.9  917.72      85  902.69   115.4   884.4
   128.9  879.62   199.8  875.66   233.6  870.37   277.9  869.38   295.1  867.58
   300.5865.6219   305.5  864.73  323.88865.6223   326.2  866.47   346.8   885.3
   376.9  905.74   383.5  907.57   399.6  908.75   422.9  915.32   459.3  922.14
   472.4  928.54   489.2  941.31   515.9  949.08   532.5  956.55   556.2  975.07
   566.4  977.98   577.8  986.08   601.8  994.34   625.7 1007.04   640.5 1013.05
#Mann= 3 ,-1,0
       0      .1       0   300.5    .045       0  323.88      .1       0
Bank Sta=300.5,323.88
XS Rating Curve= 0 ,0
Exp/Cntr(USF)=0,0
Exp/Cntr=0.3,0.1

Type RM Length L Ch R = 1 ,4416    ,151.1,149.9,141.6
XS GIS Cut Line= 3
 1632881.5167126530124.7997606121633140.15375991530462.429403655
1633225.51672626 530713.42200622
#Sta/Elev= 30
       0  943.76     5.8  940.95    73.7  923.32   118.2  910.09   127.9  904.34
   144.4   888.9   169.2  879.86   191.8  874.71   206.4  868.61     223  867.03
  229.74 861.512   243.6  860.59   251.6  861.49   278.1  864.49   342.8  861.16
   375.2  877.39   402.2  887.07   435.8  907.93   445.3  909.97   463.6  908.22
   470.5     909     519  926.72   536.3  938.55   564.1  948.41   581.4  960.18
   591.8  968.91   605.7   973.6   619.5  983.28   650.7  993.05   690.4 1010.36
#Mann= 3 ,-1,0
       0      .1       0  229.74    .045       0   251.6      .1       0
Bank Sta=229.74,251.6
XS Rating Curve= 0 ,0
Exp/Cntr(USF)=0,0
Exp/Cntr=0.3,0.1

Type RM Length L Ch R = 1 ,4266    ,249.7,257.6,258.6
XS GIS Cut Line= 4
1632777.14426204 530255.744250051632942.06991554530396.450052335
1633101.22893779530474.8762372151633213.10158387530718.228075593
#Sta/Elev= 30
       0  943.62    40.4  930.16    66.1  913.98   100.7  906.09   141.7  885.91
   182.7  872.08   228.1  869.23     261  864.06  317.69860.3042   326.8  859.01
   334.2  860.29   337.8  862.66   348.8  874.39   356.1  878.48   374.4  884.72
   385.4  891.26   398.7  895.94   418.5   905.7   428.4  908.22   452.9  909.29
   472.9  916.34     510  937.21   534.8  945.71   550.4  955.04   564.8  966.23
   575.7  968.54   593.7   979.7   634.4   994.3   653.5 1005.33   662.1 1008.52
#Mann= 3 ,-1,0
       0      .1       0  317.69    .045       0   334.2      .1       0
Bank Sta=317.69,334.2
XS Rating Curve= 0 ,0
Exp/Cntr(USF)=0,0
Exp/Cntr=0.3,0.1

Type RM Length L Ch R = 1 ,4008    ,376.5,375,359.2
XS GIS Cut Line= 2
 1632671.0382472530304.1839524761633038.04340738530855.600188616
#Sta/Elev= 30
       0  992.29       9   985.8    36.5  972.45    57.4  948.76      76  936.97
    91.7  922.52     104  914.19   118.2  905.99   135.1  902.51   167.9  882.48
   186.3  875.22   209.9  871.35   237.5  860.06370.5603855.2512   375.5  854.75
  382.21855.2648   387.3  857.52   390.4  861.11   397.4  873.78   403.1  880.45
   428.2  900.58   436.4   903.1   473.2  906.68     511  919.39     530  931.38
   544.2  934.85   584.3  962.41   604.1  971.19   655.4  986.59   662.4  991.02
#Mann= 3 ,-1,0
       0      .1       0370.5603    .045       0  382.21      .1       0
Bank Sta=370.5603,382.21
XS Rating Curve= 0 ,0
Exp/Cntr(USF)=0,0
Exp/Cntr=0.3,0.1

Type RM Length L Ch R = 1 ,3633    ,497.6,502.6,500.4
XS GIS Cut Line= 6
1632301.96885981530538.9251120541632525.30863622530664.557406724
1632632.74182031530713.116692811 1632727.1432063530772.726153642
1632821.03967205530850.3749484721632910.01718439530929.160880148
#Sta/Elev= 30
       0 1017.17    18.2 1008.92    52.8   999.9    78.4   984.5   113.7  971.35
   120.2  967.14   146.7  944.73   155.1   940.9   177.6  936.12   188.9   928.3
   211.8   917.4   256.3  891.23   283.6  870.04   294.8   854.8  300.28850.1032
   307.1  849.06  325.02850.1038   408.7  853.03   426.5  851.18   476.5  852.55
   499.9   863.7   526.7  871.35   560.5   883.7   586.1  896.44   604.8  903.02
   616.3  904.84   651.1  930.14   673.3  940.52   708.3   963.5   726.5  970.56
#Mann= 3 ,-1,0
       0      .1       0  300.28    .045       0  325.02      .1       0
#XS Ineff= 1 ,-1
  405.78726.4833  858.93
Permanent Ineff=
       F
Bank Sta=300.28,325.02
XS Rating Curve= 0 ,0
Exp/Cntr(USF)=0,0
Exp/Cntr=0.3,0.1

Type RM Length L Ch R = 1 ,3131    ,298.2,305.3,303
XS GIS Cut Line= 6
1632204.38112848530806.4938026371632265.96761946530878.103895649
1632325.18961389530943.3688569811632377.25282997530997.891385734
1632512.77388439  531119.82290041632680.91363998531244.606771559
#Sta/Elev= 30
       0  972.18    11.9  967.94    35.3  947.43    48.3  939.05   109.2  904.83
   131.4  900.31   144.7  895.32   183.1  874.07   207.3   864.9   240.1  849.05
   263.4  845.03   291.8  844.84  299.96840.8881   306.6  839.85  314.45840.8898
   336.3   843.6     379  844.28   394.9  850.59   409.2  851.82     440   866.2
   456.5  877.54   487.4  904.77   497.6  907.11   530.5  905.33   542.8  907.35
   564.1  919.23   583.4  938.21   615.2   950.2     642  969.08   649.7  972.83
#Mann= 3 ,-1,0
       0      .1       0  299.96    .045       0  314.45      .1       0
#XS Ineff= 2 , 0
          287.98  846.69
Permanent Ineff=
       F       F
Bank Sta=299.96,314.45
XS Rating Curve= 0 ,0
Exp/Cntr(USF)=0,0
Exp/Cntr=0.3,0.1

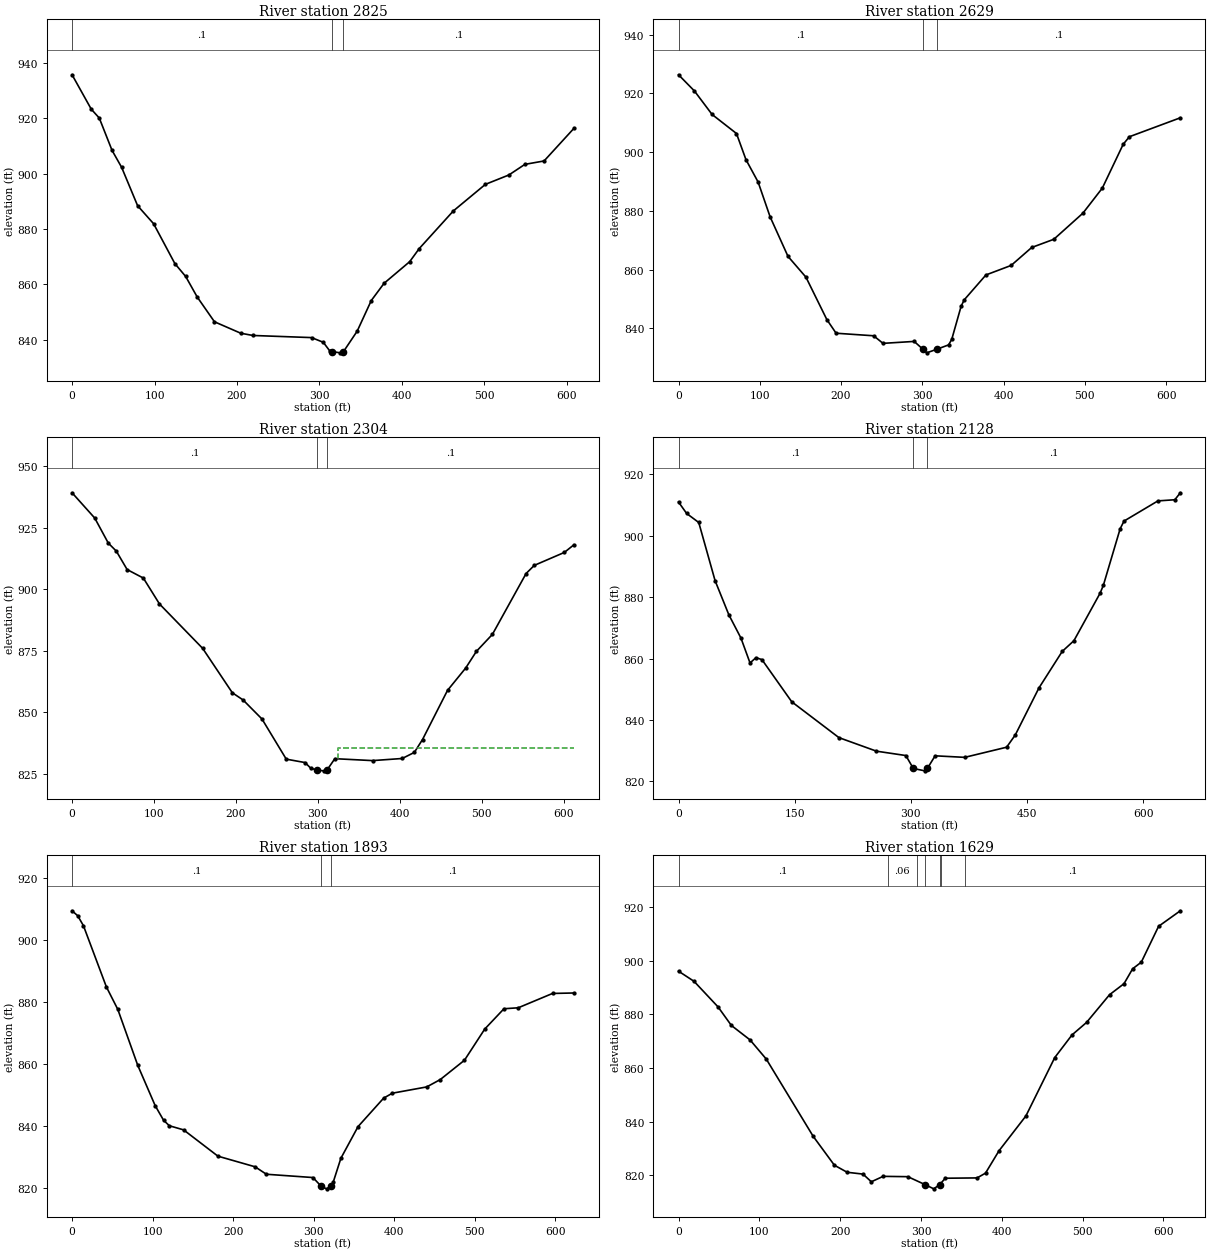
Type RM Length L Ch R = 1 ,2825    ,196.4,196.8,196
XS GIS Cut Line= 2
1632167.03467672530966.1932189651632492.27267872531480.576725679
#Sta/Elev= 30
       0  935.73    23.3  923.28      33  920.09    48.5  908.39    60.1  902.27
    79.5  888.38    98.9  881.87   124.7  867.45   137.8   862.8   151.7  855.41
   172.7  846.42   204.6  842.28   219.3  841.47   290.5   840.7   304.7     839
   312.4  835.94   315.7835.6285   325.3  835.19   329.2835.6428   345.8  843.03
   362.9   854.1   378.4  860.33   409.5  868.16   421.1   872.9   462.4  886.49
   501.3  896.11   529.8   899.5   549.2  903.34   572.5  904.57   608.6  916.33
#Mann= 3 ,-1,0
       0      .1       0   315.7    .045       0   329.2      .1       0
Bank Sta=315.7,329.2
XS Rating Curve= 0 ,0
Exp/Cntr(USF)=0,0
Exp/Cntr=0.3,0.1

Type RM Length L Ch R = 1 ,2629    ,318.4,324.8,328.3
XS GIS Cut Line= 6
1631997.16796023531049.0920707291632054.67768772531128.981674731
1632094.37052172531207.2708882241632133.52365863531271.254356056
 1632270.3271908531495.2663752291632316.89337064531576.677301645
#Sta/Elev= 30
       0  926.37    19.6  920.84    41.3  912.85    71.3  906.37      83  897.45
    97.9  889.86   112.7  877.99   134.7  864.52   156.8  857.44   182.5     843
   193.9  838.35   240.1  837.48   251.6   834.9     290  835.56  300.48832.9582
   305.4  831.67  318.52832.9604   332.3  834.37   336.2  836.25   347.7  847.49
   351.5   849.7   378.3   858.2   409.3  861.44   434.6  867.55   461.8  870.34
   497.6  879.23   521.5  887.77   547.2   902.7   554.8  905.27   617.5  911.72
#Mann= 3 ,-1,0
       0      .1       0  300.48    .045       0  318.52      .1       0
Bank Sta=300.48,318.52
XS Rating Curve= 0 ,0
Exp/Cntr(USF)=0,0
Exp/Cntr=0.3,0.1

Type RM Length L Ch R = 1 ,2304    ,183.3,176.2,165.2
XS GIS Cut Line= 3
1631875.30325443531064.8477020751631845.31677198531436.218754008
1631954.88276556531649.584109932
#Sta/Elev= 30
       0  939.21    27.7  928.92    44.2  918.76      54   915.5    67.2     908
      87  904.54   106.7  894.01   159.4  875.96   195.6  857.92   208.7     855
   231.8  847.25   261.4  830.94   284.4  829.55     291  827.35   298.8 826.452
   307.5  826.19  310.99 826.447   320.7  831.13   366.7  830.35   402.9  831.21
   417.7  833.68   427.7  838.91   458.2  858.89   480.4  867.98   493.5  874.77
     513  881.66   554.1  906.39   564.1   909.7   600.7  914.95   612.4  918.05
#Mann= 3 ,-1,0
       0      .1       0   298.8    .045       0  310.99      .1       0
#XS Ineff= 2 , 0
                          324.48          835.42
Permanent Ineff=
       F       F
Bank Sta=298.8,310.99
XS Rating Curve= 0 ,0
Exp/Cntr(USF)=0,0
Exp/Cntr=0.3,0.1

Type RM Length L Ch R = 1 ,2128    ,228.7,234.4,237.7
XS GIS Cut Line= 6
1631450.60507697531257.2704601441631606.81670681531355.142311648
1631759.44271389531441.5906295631631806.36223947531506.991089314
1631855.35722022531594.1021355541631905.52739547531689.337837473
#Sta/Elev= 30
       0  910.93    10.5  907.21    26.1  904.28    47.2  885.34      65  874.21
    80.6  866.65    92.3  858.56     100  860.28   107.7  859.64   146.2  845.91
   207.1  834.25   255.6  829.84   293.5  828.42  303.17824.2065     318  823.44
  321.24824.2072   331.3  828.33   369.5  827.83   423.6  831.13   434.8  835.12
   465.3   850.4   495.4  862.31   510.5   865.8   544.3  881.26   548.5  883.81
   570.2  902.24   575.2  904.74     619  911.31   640.8  911.68   647.9  913.95
#Mann= 3 ,-1,0
       0      .1       0  303.17    .045       0  321.24      .1       0
Bank Sta=303.17,321.24
XS Rating Curve= 0 ,0
Exp/Cntr(USF)=0,0
Exp/Cntr=0.3,0.1

Type RM Length L Ch R = 1 ,1893    ,263.4,264.1,263.1
XS GIS Cut Line= 2
1631439.28581408531272.9780009961631678.02434747531848.487798867
#Sta/Elev= 30
       0  909.32       7  907.72    14.1  904.52    42.6   884.8    56.8  877.54
    81.6  859.49   103.2  846.53   113.6  841.83   120.8  840.05   138.5  838.72
   181.1  830.25   227.3  826.82   241.3  824.42   299.1  823.36   309.4820.5375
     316  819.72  321.39 820.546   324.2  821.81   333.8  829.57   355.1  839.77
   386.9  848.95   397.7  850.54   440.4  852.56   457.2  854.93   487.3  861.17
   512.4  871.19   536.3  877.75     554  878.06   596.6  882.68   623.1  882.83
#Mann= 3 ,-1,0
       0      .1       0   309.4    .045       0  321.39      .1       0
Bank Sta=309.4,321.39
XS Rating Curve= 0 ,0
Exp/Cntr(USF)=0,0
Exp/Cntr=0.3,0.1

Type RM Length L Ch R = 1 ,1629    ,225.8,236,243.7
XS GIS Cut Line= 6
1631243.62025473531358.7902702241631254.02148063531457.238236055
1631278.71762547531543.4293366371631301.23496889531616.073876396
 1631339.6892883 531708.389964731631440.63035938531943.921317816
#Sta/Elev= 30
       0  896.09    19.2  892.31    48.9  882.78    65.4  875.87    88.5  870.49
   108.6  863.34   166.6  834.59   192.9   823.8   208.7  821.18   228.3   820.5
   238.6  817.64   253.2  819.66   283.8  819.54  304.94 816.604   315.9  815.01
  323.26816.6057   330.1  818.96   369.5  819.08   379.9  820.86   396.6  829.19
   429.9  842.16   465.6  863.91     487  872.36   504.9  876.98   533.4  887.32
   551.3  891.43     562  896.99   572.7  899.44   594.1   912.8     621  918.59
#Mann= 7 ,-1,0
       0      .1       0  258.66     .06       0  294.71      .1       0
  304.94    .045       0  323.26      .1       0  324.71     .06       0
  354.71      .1       0
Bank Sta=304.94,323.26
XS Rating Curve= 0 ,0
Exp/Cntr(USF)=0,0
Exp/Cntr=0.3,0.1

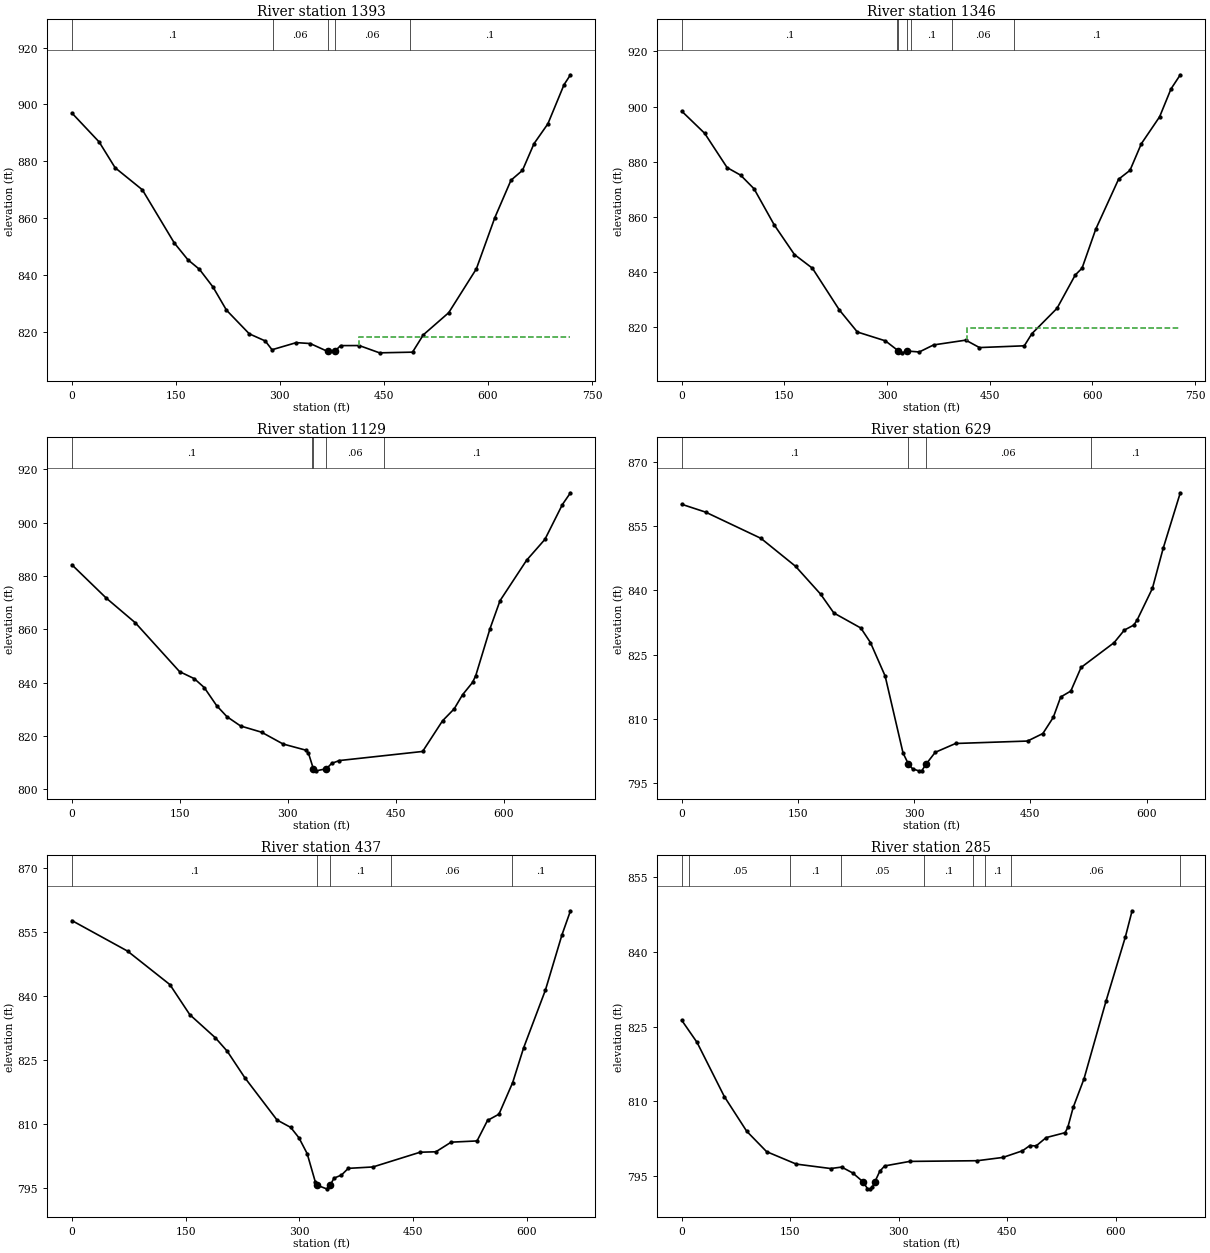
Type RM Length L Ch R = 1 ,1393    ,47.3,47.4,47.5
XS GIS Cut Line= 4
1631150.36240652531351.7295890911631151.11473455531668.459689669
1631052.55976264531690.2772025361631102.21341261531987.446774337
#Sta/Elev= 30
       0     897    39.3  886.83    62.3  877.77   101.6  870.02   147.6  851.35
   167.2  845.45   183.9  842.08   203.5  835.84   222.9  827.72   255.8   819.4
   278.8   816.9   288.6  813.81   323.6  816.31   343.7  815.99   368.9   813.2
  378.91813.2023   387.4  815.26   414.4  815.28   443.6  812.72   491.2  812.96
   506.8  819.05   543.4  826.83   583.3  842.25   609.9  860.23   633.2  873.38
   649.8  876.86   666.4  886.23   686.4   893.2   709.7  906.95     719  910.44
#Mann= 5 ,-1,0
       0      .1       0     290     .06       0   368.9    .045       0
  378.91     .06       0  487.67      .1       0
#XS Ineff= 2 , 0
                          413.72          818.28
Permanent Ineff=
       F       F
Bank Sta=368.9,378.91
XS Rating Curve= 0 ,0
Exp/Cntr(USF)=0,0
Exp/Cntr=0.3,0.1

Type RM Length L Ch R = 1 ,1346    ,232.3,217.1,197.8
XS GIS Cut Line= 4
1631125.91174555531350.9772610611631127.41640161531625.576991966
1631028.86142969531647.3945048331631089.80000011531994.970054636
#Sta/Elev= 30
       0  898.36    33.5  890.34    66.3  877.91      86  875.17   105.7  870.22
   135.2  857.12   164.7  846.39     191  841.43   230.3  826.32   256.6  818.33
   297.5  815.13   316.7  811.45   322.2  810.78  329.06811.4526     347  811.09
     368  813.65     415  815.38     435  812.69   500.5  813.33   511.6  817.73
   548.3  826.91   574.9  838.97   584.9  841.47   604.9   855.6   638.2  873.68
   654.9  876.91   671.5  886.56   698.2  896.32   714.8  906.41   728.4  911.54
#Mann= 7 ,-1,0
       0      .1       0   314.6     .06       0   316.7    .045       0
  329.06     .06       0   334.6      .1       0  395.54     .06       0
  485.54      .1       0
#XS Ineff= 2 , 0
                          416.61          819.83
Permanent Ineff=
       F       F
Bank Sta=316.7,329.06
XS Rating Curve= 0 ,0
Exp/Cntr(USF)=0,0
Exp/Cntr=0.3,0.1

Type RM Length L Ch R = 1 ,1129    ,497.5,499.3,504.5
XS GIS Cut Line= 6
1630766.16714139531400.2688618151630819.85994738531600.097858474
1630859.47896264531676.9772978871630951.21303114531716.788241893
1630990.76150846531796.7155754721631059.21511172531995.421214804
#Sta/Elev= 30
       0   884.2    47.8  871.69    88.2  862.43   149.6  844.13   170.2  841.47
   183.9  838.16   201.1  831.39   215.4  827.24   234.4  823.74   263.6   821.4
   293.5  816.97   325.2  814.66   328.8   813.5  335.54807.7087   339.5  806.91
  353.77807.7103     361   809.7   371.7  810.77   487.4  814.18   515.1  825.68
   531.3  830.16   542.9  835.45   556.8  840.07   561.3  842.67   581.1  860.26
     595  870.74   631.9   885.9   657.4  893.74   681.7  906.81   692.9  911.21
#Mann= 5 ,-1,0
       0      .1       0  333.52     .06       0  335.54    .045       0
  353.77     .06       0  433.52      .1       0
Bank Sta=335.54,353.77
XS Rating Curve= 0 ,0
Exp/Cntr(USF)=0,0
Exp/Cntr=0.3,0.1

Type RM Length L Ch R = 1 ,629     ,189.2,192,193.3
XS GIS Cut Line= 6
1630389.76927213531459.1601482331630477.98530306531618.313045144
1630517.86153564531681.9395583121630573.94639722531764.741886139
1630582.52183938531844.8988780531630567.81747247532050.267889887
#Sta/Elev= 30
       0  860.14    30.7  858.32   102.3  852.18   146.9  845.66   179.3  839.14
   196.4  834.74   231.2  831.23   243.6  827.84   262.6  820.01   285.7  802.03
  292.64799.4501     298  798.34   305.9  797.86   309.9  797.88  315.54799.4493
   327.2  802.18   353.5  804.25   446.4  804.82   466.2  806.58   479.6  810.34
   489.2  815.11   502.3  816.51   515.5  822.01   558.2  827.82   571.4  830.75
   583.6  831.92   587.8  833.07   607.6  840.49   621.5  849.85   643.6  862.83
#Mann= 4 ,-1,0
       0      .1       0  292.64    .045       0  315.54     .06       0
   527.7      .1       0
Bank Sta=292.64,315.54
XS Rating Curve= 0 ,0
Exp/Cntr(USF)=0,0
Exp/Cntr=0.3,0.1

Type RM Length L Ch R = 1 ,437     ,150,152,153.2
XS GIS Cut Line= 3
1630360.54132989531468.6590211141630342.60069937531739.049952646
1630505.34784773532090.173721554
#Sta/Elev= 30
       0   857.6    73.4  850.46   129.3  842.62   155.6  835.58   189.3  830.18
     205  827.03     228  820.88   270.7  810.94   288.8   809.2   299.6  806.78
   310.5  803.07   321.2  796.47   323.3 795.695   336.1  794.83  340.94 795.713
   345.9  797.33   355.8  798.06   364.7  799.62   397.3  799.95   459.6   803.4
   480.4   803.5   500.5  805.75   534.7  806.04   548.5  810.83   563.6   812.3
   581.7  819.69   596.1  827.79   624.9  841.32   646.8  854.28     658  859.89
#Mann= 5 ,-1,0
       0      .1       0   323.3    .045       0  340.94      .1       0
  420.99     .06       0  580.99      .1       0
Bank Sta=323.3,340.94
XS Rating Curve= 0 ,0
Exp/Cntr(USF)=0,0
Exp/Cntr=0.3,0.1

Type RM Length L Ch R = 1 ,285     ,260.7,273.3,284.6
XS GIS Cut Line= 4
1630249.19762496531613.5779888241630207.37494907531748.903060864
1630277.03495184532014.5398714131630458.15095903532112.992675323
#Sta/Elev= 30
       0  826.27    21.2  821.82    58.9  810.94    89.8  803.98   117.3  799.88
   158.3  797.38   205.8  796.49     221  796.78   236.3   795.6250.1262793.8721
   256.7  792.47   260.1  792.41   263.5  792.75267.0562793.8647   273.6  795.91
   280.4  797.01   315.1  797.92   408.5  798.06   443.9  798.72   470.9  800.05
   481.2  801.11   489.7  801.02   503.6   802.7   529.8  803.69   533.5  804.74
     541  808.77   555.9  814.49   586.4  830.14   613.1  843.01   622.4  848.26
#Mann= 9 ,-1,0
       0      .1       0      10     .05       0     150      .1       0
     220     .05       0  334.38      .1       0  402.87    .045       0
   419.8      .1       0  454.38     .06       0     689      .1       0
Bank Sta=250.1262,267.0562
XS Rating Curve= 0 ,0
Exp/Cntr(USF)=0,0
Exp/Cntr=0.3,0.1

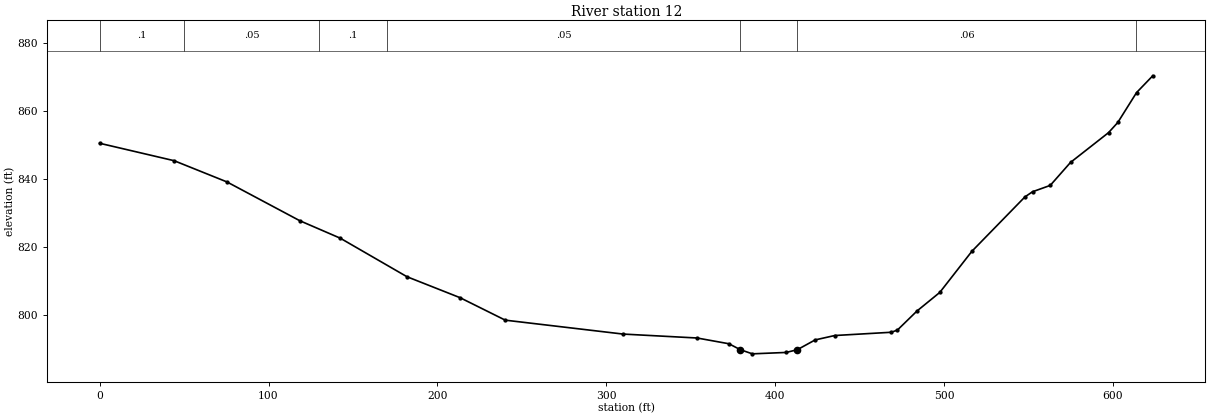
Type RM Length L Ch R = 1 ,12      ,390.6,389.9,387
XS GIS Cut Line= 3
1630325.91513375531519.9220178261630109.96075992531703.927920055
1629862.30898073531936.679294731
#Sta/Elev= 30
       0  850.55    44.1  845.42    75.4  839.17   118.5  827.76   142.5  822.61
     182  811.27   213.4  805.11   240.2  798.49   309.9   794.4   353.8  793.24
   372.6  791.55  379.47789.7838   386.5  788.58   406.5  788.99  413.07 789.784
   423.7  792.68   435.3  793.97   468.8  794.93   472.4  795.58     484  801.19
   497.5  806.66   516.5  818.76   547.9  834.76   552.4  836.28   562.9  838.15
   574.9  844.91   597.4  853.67   602.9  856.67     614  865.46   623.6  870.41
#Mann= 7 ,-1,0
       0      .1       0      50     .05       0     130      .1       0
     170     .05       0  379.47    .045       0  413.07     .06       0
  613.72      .1       0
Bank Sta=379.47,413.07
XS Rating Curve= 0 ,0
Exp/Cntr=0.3,0.1
LCMann Table=0

Chan Stop Cuts=-1
Use User Specified Reach Order=0
Composite Channel Slope=5